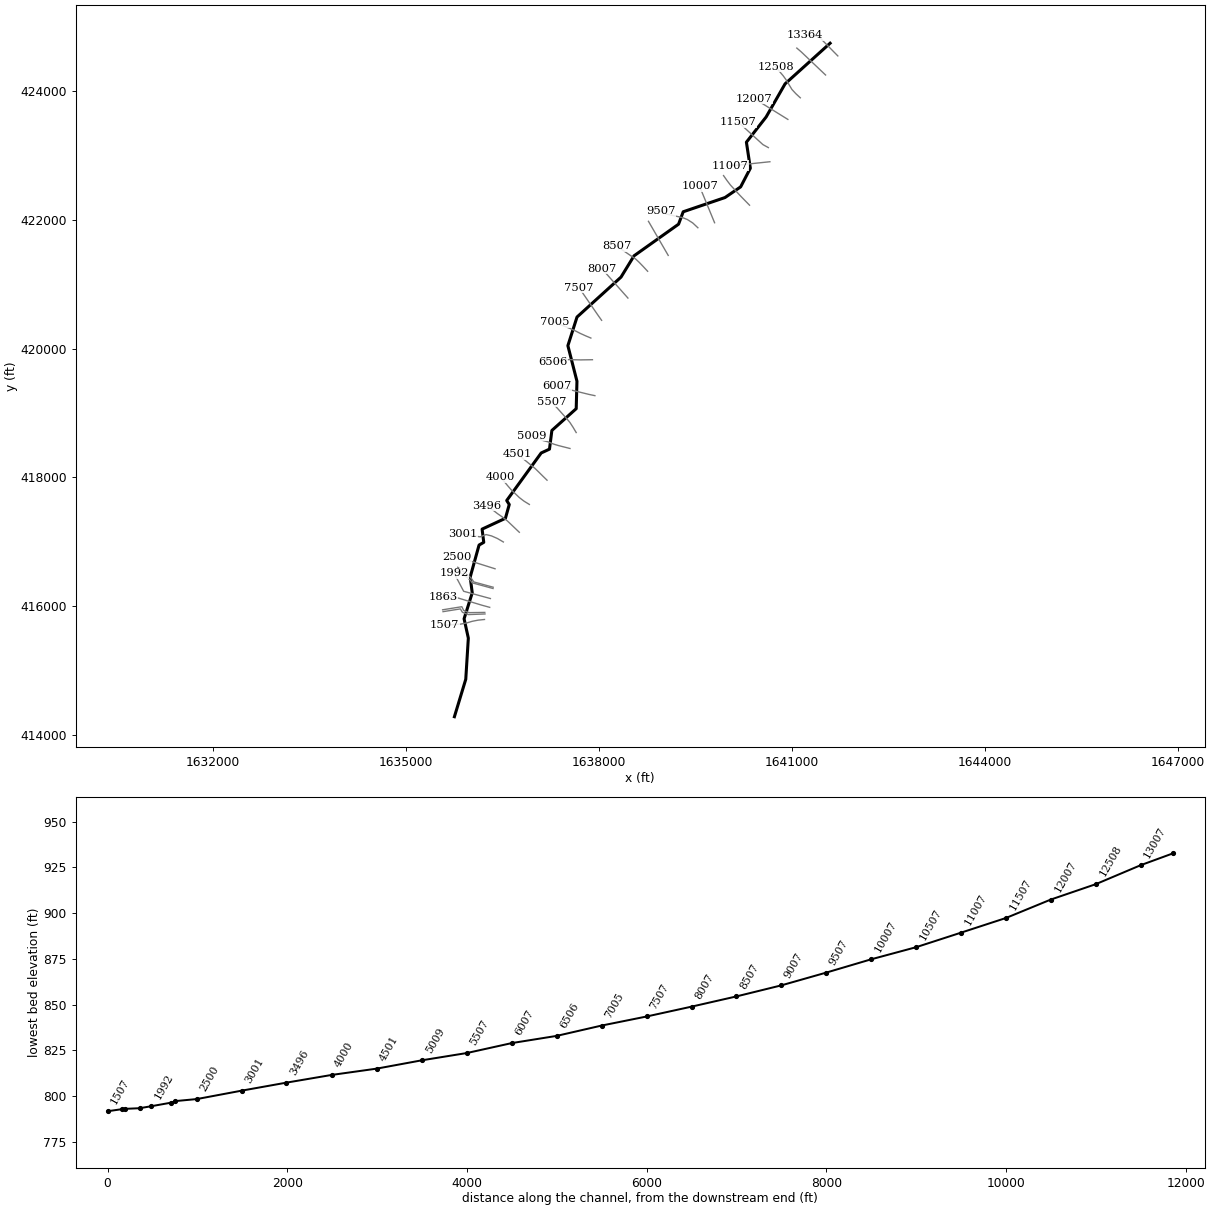
--- RUSHRN1.prj (project) ---

Proj Title=RUSHRN1
Current Plan=p01
Default Exp/Contr=0,0
English Units
Geom File=g01
Flow File=f01
Plan File=p01
BEGIN DESCRIPTION:
---------- MODELED AS PART OF WVEMD CTP PROGRAM, 2023----------
Stream Name: Rush Run
Flood Zone:  AFH
Wetzel County, WV
HEC-RAS Version: RAS 6.3
Vertical Datum: NAVD88
Projection: NAD 1983 StatePlane West Virginia S FIPS 4702 (US Feet)
Terrain: 1-meter West Virginia FEMA R3 South Central (collected 2018-2020)
Land Use: 2019 NLCD
Hydrologic Method:
WV SIR2010-5033 regression equations
Additional Model Notes:
Leveraged XS
END DESCRIPTION:
DSS Export Rating Curves= 0
DSS Export Rating Curve Sorted= 0
DSS Export Volume Flow Curves= 0
DXF OffsetX= 0
DXF OffsetY= 0
DXF ScaleX= 0
DXF ScaleY= 0

--- RUSHRN1.p01 (plan) ---

Plan Title=Floodplain
Program Version=6.30
Short Identifier=Floodplain
Geom File=g01
Flow File=f01
Subcritical Flow
K Sum by GR= 0
Std Step Tol= 0.01
Critical Tol= 0.01
Num of Std Step Trials= 20
Max Error Tol= 0.3
Flow Tol Ratio= 0.001
Split Flow NTrial= 30
Split Flow Tol= 0.02
Split Flow Ratio= 0.02
Log Output Level= 0
Friction Slope Method= 1
Unsteady Friction Slope Method= 2
Unsteady Bridges Friction Slope Method= 1
Parabolic Critical Depth
Global Vel Dist= 0 , 0 , 0
Global Log Level= 0
CheckData=True
Encroach Param=-1 ,0,0, 0
Mapping Interval=1HOUR
Computation Time Step Use Courant=        0
Computation Time Step Use Time Series=    0
Computation Time Step Count To Double=0
Computation Time Step Max Doubling=0
Computation Time Step Max Halving=0
Computation Time Step Residence Courant=0
Run HTab= 0
Run UNet= 0
Run Sediment= 0
Run PostProcess= 0
Run WQNet= 0
Run RASMapper= 0
UNET Theta= 0
UNET Theta Warmup= 0
UNET ZTol= 0
UNET ZSATol= 0
UNET MxIter= 0
UNET Max Iter WO Improvement= 0
UNET MaxInSteps= 0
UNET DtIC= 0
UNET DtMin= 0
UNET MaxCRTS= 0
UNET WFStab= 0
UNET SFStab= 0
UNET WFX= 1
UNET SFX= 1
UNET Gravity=32.17405
UNET 1D Methodology=Finite Difference
UNET DSS MLevel= 1
UNET Pardiso=0
UNET DZMax Abort= 0
UNET Use Existing IB Tables= 0
UNET Froude Reduction=False
UNET Froude Limit= 0
UNET Froude Power= 0
UNET D1 Cores= 0
UNET WindReference=Eulerian
UNET WindDragFormulation=Hsu (1988)
UNET D2 Coriolis=0
UNET D2 Cores= 0
UNET D2 Theta= 1
UNET D2 Theta Warmup= 1
UNET D2 Z Tol= 0.01
UNET D2 Volume Tol= 0.01
UNET D2 Max Iterations= 20
UNET D2 Equation= 0
UNET D2 RampUpFraction=0.1
UNET D2 TimeSlices= 1
UNET D2 Turbulence Formulation=Non-Conservative (original)
UNET D2 Eddy Viscosity=0.3
UNET D2 Transverse Eddy Viscosity=0.1
UNET D2 Smagorinsky Mixing=0
UNET D2 BCVolumeCheck=0
UNET D2 Cores=0
UNET D2 SolverType=PARDISO (Direct)
UNET D2 Minimum Iterations= 3
UNET D2 Maximum Iterations= 30
UNET D2 Restart Number= 10
UNET D2 Relaxation Coeff=1.3
UNET D2 SOR Precondition Iterations= 10
UNET D2 ILUT Maximum Fill= 8
UNET D2 ILUT Tolerance=1E-08
UNET D2 Convergence Tolerance=0.00001
UNET D1D2 MaxIter= 0
UNET D1D2 ZTol=0.01
UNET D1D2 QTol=0.1
UNET D1D2 MinQTol=1
Write IC File= 0
Write IC File at Fixed DateTime=0
Write IC File at Sim End=0
Echo Input=False
Echo Parameters=False
Echo Output=False
Write Detailed= 0
HDF Write Warmup=0
HDF Write Time Slices=0
HDF Flush=0
HDF Compression= 1
HDF Chunk Size= 1
HDF Spatial Parts= 1
HDF Use Max Rows=0
HDF Fixed Rows= 1
Calibration Method= 0
Calibration Iterations= 20
Calibration Max Change=0.05
Calibration Tolerance=0.2
Calibration Maximum=1.5
Calibration Minimum=0.5
Calibration Optimization Method= 1
WQ AD Non Conservative
WQ ULTIMATE=-1
WQ Max Comp Step=1HOUR
WQ Output Interval=15MIN
WQ Output Selected Increments= 0
WQ Output face flow=0
WQ Output face velocity=0
WQ Output face area=0
WQ Output face dispersion=0
WQ Output cell volume=0
WQ Output cell surface area=0
WQ Output cell continuity=0
WQ Output cumulative cell continuity=0
WQ Output face conc=0
WQ Output face dconc_dx=0
WQ Output face courant=0
WQ Output face peclet=0
WQ Output face adv mass=0
WQ Output face disp mass=0
WQ Output cell mass=0
WQ Output cell source sink temp=0
WQ Output nsm pathways=0
WQ Output nsm derived pathways=0
WQ Create Restart=0
WQ Fixed Restart=0
WQ System Summary=0
WQ Write To DSS=0
Sorting and Armoring Iterations= 10
XS Update Threshold= 0.02
Bed Roughness Predictor= 0
Hydraulics Update Threshold= 0.02
Energy Slope Method= 1
Volume Change Method= 1
Sediment Retention Method= 0
Sediment TS Multiplier= 1
Warm Up Method= 0
XS Weighting Method= 0
Number of US Weighted Cross Sections= 1
Number of DS Weighted Cross Sections= 1
Upstream XS Weight=0
Main XS Weight=1
Downstream XS Weight=0
Number of DS XS's Weighted with US Boundary= 1
Upstream Boundary Weight= 1
Weight of XSs Associated with US Boundary= 0
Number of US XS's Weighted with DS Boundary= 1
Downstream Boundary Weight= 0.5
Weight of XSs Associated with DS Boundary= 0.5
Percentile Method= 0
Sediment Output Level= 3
Mass or Volume Output= 0
Output Increment Type= 1
Profile and TS Output Increment= 1
Transport Output Increment 1
XS Output Flag= 0
XS Output Increment= 10
Read HDF5 Sediment Hotstart= 0
Sediment Hotstart Type= 0
Write Gradation File= 0
Read Gradation Hotstart= 0
Write HDF5 File= 1
Write Binary Output= 1
Write DSS Sediment File= 0
DSS Sediment Output Type= 1
SV Curve= 0
Specific Gage Flag= 0
Subcell Erosion Methods= 0
Subcell Deposition Methods= 0
Advection Scheme= 1
Matrix Solver= 0
Implicit Weighting Factor= 1
Maximum Outer Loop Convergence Iterations= 5
Convergence Maximum Absolute= 0.001
Convergence RMSE= 0.0001
Grain Fractions Max Abs Error= 0.001
Max Subgrid Regions= 1
Max Subgrid Length Scale= 3.402823E+38
Initial Layer Thickness= 3.402823E+38
Min Layer Thickness= 3.402823E+38
Max Layer Thickness= 3.402823E+38
Number of Layers= 5

--- RUSHRN1.f01 (steady flow) ---

Flow Title=Flow
Program Version=4.00
Number of Profiles=1
Profile Names=F01pct
River Rch & RM=RUSHRN1,Main,13364
     900
River Rch & RM=RUSHRN1,Main,9507
    1170
River Rch & RM=RUSHRN1,Main,7005
    1350
River Rch & RM=RUSHRN1,Main,5507
    1510
Boundary for River Rch & Prof#=RUSHRN1,Main      ,1
Up Type=0
Dn Type=3
Dn Slope=0.010425

--- RUSHRN1.g01 (geometry) ---

Geom Title=Geometry
Program Version=6.30

River Reach=RUSHRN1         ,Main
Reach XY= 30
     1641591.669      424747.653     1640891.492      424115.974
     1640597.207      423601.375     1640290.526      423209.127
     1640351.702      422804.485     1640200.961      422514.598
     1639957.855      422348.662     1639308.109      422127.549
     1639235.737      421934.424     1638544.006      421443.015
     1638341.285      421111.944     1637657.152      420490.986
     1637515.207       420045.96     1637656.352      419493.375
     1637644.757      419066.741     1637266.504      418728.073
     1637229.319      418437.786     1637100.569      418378.209
     1636564.378      417638.898     1636603.962      417576.522
     1636544.386      417362.605     1636181.727      417194.271
     1636207.717      416988.751     1636134.545      416946.767
     1635996.599      416448.561     1636028.586      416203.857
     1635901.836      415800.414      1635967.81      415499.731
     1635927.826       414859.98     1635751.425      414278.081

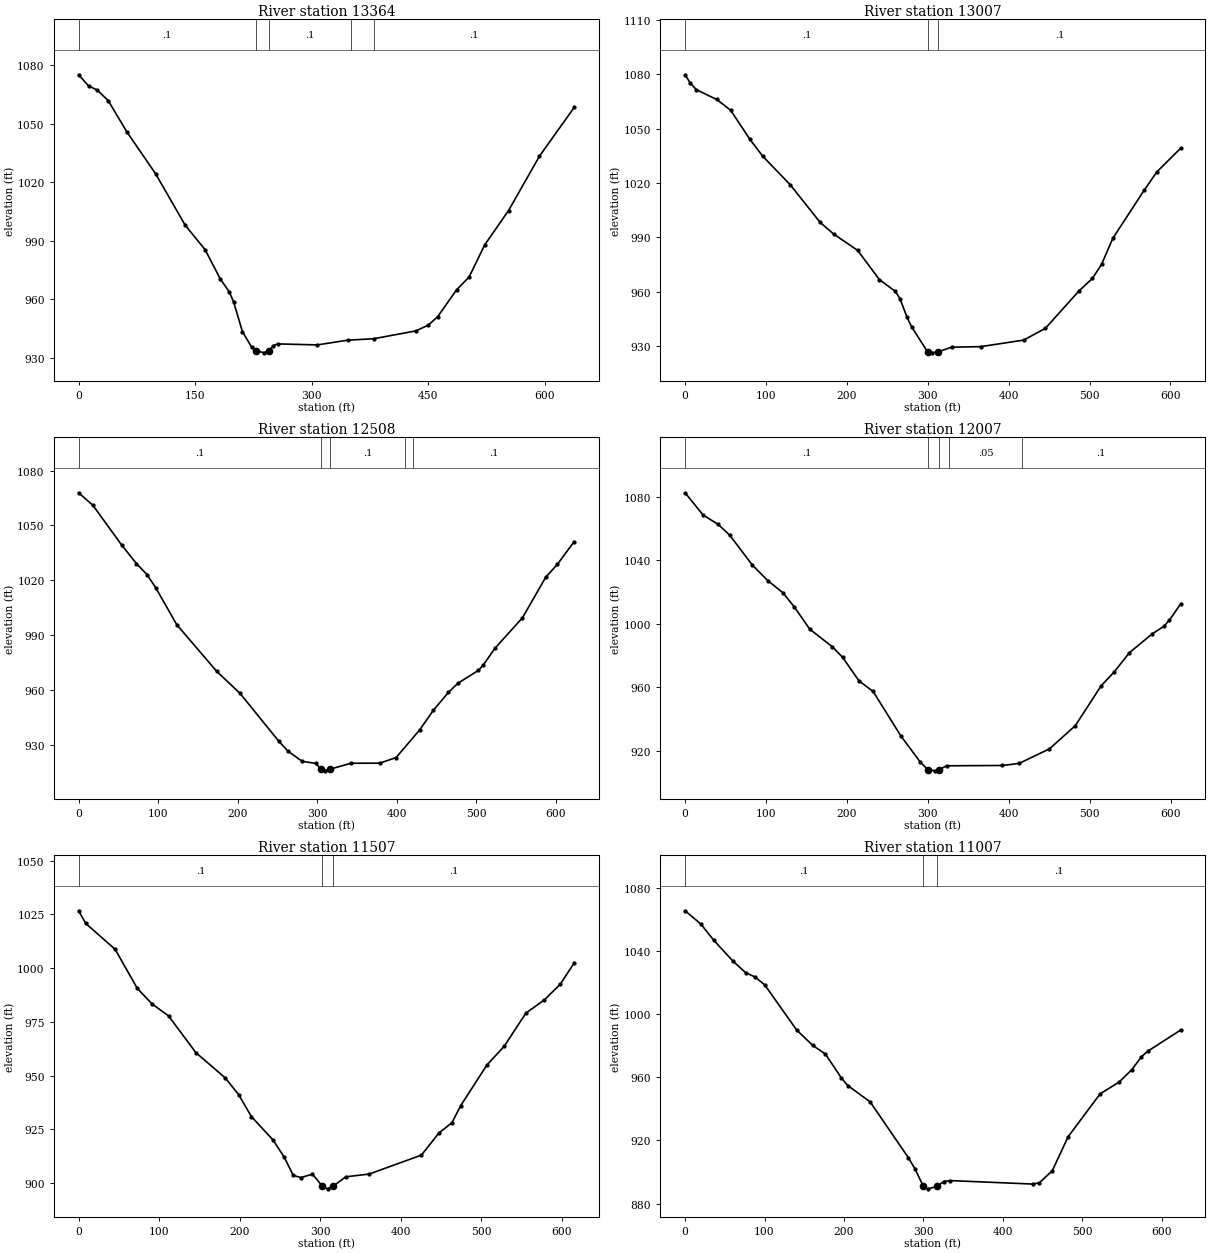
Type RM Length L Ch R = 1 ,13364   ,357.3,357.7,357.7
XS GIS Cut Line= 3
1641711.65175674424550.0174320721641414.58553958 424851.63638819
1641201.74499319424875.538267732
#Sta/Elev= 30
       0 1074.99    12.8 1069.27    24.1 1067.15    38.2 1061.66      62 1045.79
      99 1024.33   137.2  997.91   162.7  985.46   182.5  970.25   193.8  963.87
   199.5  958.55   210.8  943.43   222.5  935.64   228.1  933.79   238.8  932.63
   244.7  933.76   250.6  936.27     256  937.21   306.9  936.69     346   939.1
   379.7  939.86   433.9  943.86     450  946.86   462.1  951.22   486.2  964.89
   502.3  971.42   522.4  987.88   553.1 1005.49   592.9 1033.34 637.525 1058.26
#Mann= 5 ,-1,0
       0      .1       0   228.1    .045       0   244.7      .1       0
     350     .05       0     380      .1       0
Bank Sta=228.1,244.7
XS Rating Curve= 0 ,0
Exp/Cntr(USF)=0,0
Exp/Cntr=0.3,0.1

Type RM Length L Ch R = 1 ,13007   ,500,498.9,496.4
XS GIS Cut Line= 6
1641520.91958201 424253.568129421641389.55435917424378.447144762
1641262.71931101424499.0200663361641208.36148009424550.694503665
  1641144.943956424610.9811284991641073.90177526424672.318276167
#Sta/Elev= 30
       0 1079.83     6.6 1075.14      14 1071.57    39.1 1066.19    56.3 1060.24
    79.8 1044.35      96 1034.82     130 1019.06   166.8  998.34   183.7  991.82
   213.3   982.8   240.3  966.63   259.8   960.2   265.6  956.18   274.3  945.88
   279.9  940.69   299.7  926.73   304.7   926.2  312.93926.7521   329.4  929.33
   365.4  929.62   418.6  933.24   445.5  939.78   486.8  960.36   503.5  967.29
   514.8  975.06   528.9  989.58   567.4 1015.96   583.3 1026.23   612.6 1039.24
#Mann= 3 ,-1,0
       0      .1       0   299.7    .045       0  312.93      .1       0
Bank Sta=299.7,312.93
XS Rating Curve= 0 ,0
Exp/Cntr(USF)=0,0
Exp/Cntr=0.3,0.1

Type RM Length L Ch R = 1 ,12508   ,498.4,501.1,503.8
XS GIS Cut Line= 6
1641128.17758533   423899.1892451641058.18953633423963.845283672
1640998.19457759 424028.891413421640907.06746326424179.508894339
1640861.71158284424242.1783884171640741.45001234424383.505533591
#Sta/Elev= 30
       0 1067.87      18    1061    54.5 1039.06    72.7 1029.16    85.9 1023.19
    97.2  1015.7   123.4   995.7   173.7  970.17   202.8  958.23   251.8   931.9
   263.4  926.51     281  921.02   298.5   919.9  304.05916.7817   309.9  915.85
     316  916.77   342.4     920   378.5  920.05     399  923.11   428.6  938.22
   445.9  949.01   464.7   958.7   476.6  963.69   502.3  970.73   508.6  973.71
   523.4  982.93   557.8  999.52     587 1021.65   601.8 1028.81   622.8 1041.17
#Mann= 5 ,-1,0
       0      .1       0  304.05    .045       0     316      .1       0
  409.82     .07       0  419.82      .1       0
Bank Sta=304.05,316
XS Rating Curve= 0 ,0
Exp/Cntr(USF)=0,0
Exp/Cntr=0.3,0.1

Type RM Length L Ch R = 1 ,12007   ,501.1,500,498.6
XS GIS Cut Line= 6
 1640934.8636675423563.2689850931640780.83674459423658.805211335
1640717.10163584423698.3382687571640568.38605401423790.580866426
1640494.02859117 423836.70249334 1640414.3591311423886.117748842
#Sta/Elev= 30
       0  1082.6    22.1 1068.69    40.9 1062.66      55 1055.99    83.3 1036.95
   102.1 1027.33   120.9 1019.62     135  1010.7     154  996.72   182.1  985.56
   194.7  978.93     215  964.07   232.4  957.45   266.8  929.33   290.5   913.1
   299.8  908.26   309.2  907.44  314.21908.2547   323.3  910.62   392.2  910.82
   412.7  912.08   450.4   921.3   482.3  935.91   514.2  960.96   530.4  969.77
   549.2  981.87   577.5  993.79   591.6  998.39   598.5 1002.29   612.5 1012.59
#Mann= 5 ,-1,0
       0      .1       0   299.8    .045       0  314.21      .1       0
  326.25     .05       0  416.25      .1       0
Bank Sta=299.8,314.21
XS Rating Curve= 0 ,0
Exp/Cntr(USF)=0,0
Exp/Cntr=0.3,0.1

Type RM Length L Ch R = 1 ,11507   ,494.2,500.1,505.7
XS GIS Cut Line= 6
 1640631.8130925423124.9827881751640547.38543984423171.437747762
1640427.28266168423280.8981587591640297.94171301423398.779484674
1640233.27156676423457.7203116721640164.17754485423521.085342422
#Sta/Elev= 30
       0 1026.64     8.8 1020.76    45.3 1008.72    72.7  990.64      91  983.36
   111.6  977.78   145.5   960.7     182  948.95   198.6  941.16   214.4  930.99
   241.5  919.99   255.2  912.11   266.5  903.59   276.1  902.61   290.2   904.2
  302.61 898.584     309  897.36   315.9898.5926   331.6  902.95   360.6  904.23
   425.5  913.04   447.2  923.32   463.4  928.11   474.2  936.01   506.7   954.9
   528.4  963.71   555.1  979.03     578  985.19   597.8  992.46   615.1  1002.4
#Mann= 3 ,-1,0
       0      .1       0  302.61    .045       0   315.9      .1       0
Bank Sta=302.61,315.9
XS Rating Curve= 0 ,0
Exp/Cntr(USF)=0,0
Exp/Cntr=0.3,0.1

Type RM Length L Ch R = 1 ,11007   ,505.6,499.9,488
XS GIS Cut Line= 6
1640655.80812326422905.3683980111640400.98415785422878.465236589
1640301.55620709422867.7844836711640226.99402025422859.650641665
1640135.10050325422849.8209369181640034.93895817422844.741550758
#Sta/Elev= 30
       0 1065.55    19.8 1057.17    35.9    1047      60 1033.77    76.1 1026.41
    88.2 1023.53   100.2 1018.67   140.5  989.99   160.6  980.28   176.7  974.75
   196.8   959.6   204.8  954.83     233  944.47   281.3  908.98   289.3  902.14
   300.1  890.88   305.4  889.35   317.5  890.91   325.5     894   333.6  894.59
   438.2  892.37   446.2  893.22   462.3  900.78   482.4  922.45   522.6  949.53
   546.6  957.06   562.7  964.95   574.7   973.1   582.7  976.59     624  989.98
#Mann= 3 ,-1,0
       0      .1       0   300.1    .045       0   317.5      .1       0
Bank Sta=300.1,317.5
XS Rating Curve= 0 ,0
Exp/Cntr(USF)=0,0
Exp/Cntr=0.3,0.1

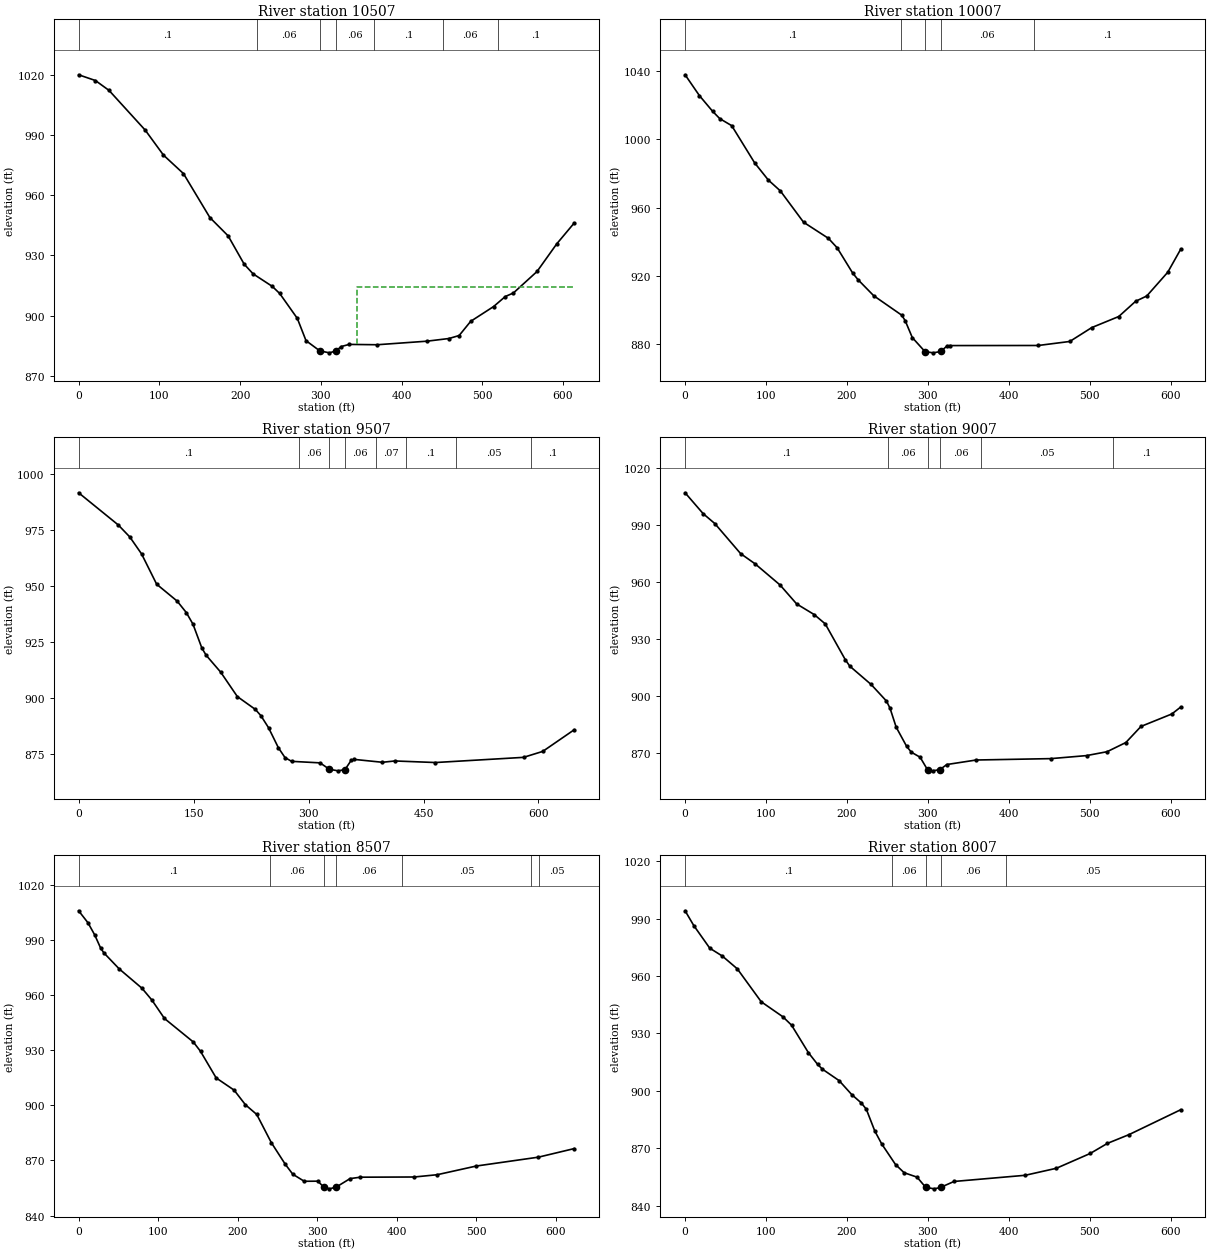
Type RM Length L Ch R = 1 ,10507   ,502.4,500,495.2
XS GIS Cut Line= 6
1640339.18802159 422229.706035421640212.24273743422359.210041508
 1640160.8517641422413.8431343441640042.48060976422542.735593095
1639989.22612309422612.6288260071639934.95392193422690.169681415
#Sta/Elev= 30
       0 1020.15    20.8 1017.28    37.7 1012.34    82.6  992.48   105.1  980.07
   129.9  970.83   162.6  948.91   185.2  939.78   205.1  925.64   216.1  920.83
   239.9  914.57   249.1  911.02   270.9  898.61   281.7  887.48   298.8  882.39
   310.7  881.41  318.82882.3725   325.2  884.54   335.2  885.62   369.8  885.45
   431.4  887.22   458.8  888.56   471.4  890.05   485.7  897.13   514.1  904.51
   528.6  909.52   538.6  911.27   567.9     922   592.3  935.78   613.9  946.17
#Mann= 7 ,-1,0
       0      .1       0  221.35     .06       0   298.8    .045       0
  318.82     .06       0  366.35      .1       0  451.35     .06       0
  519.22      .1       0
#XS Ineff= 2 , 0
                          344.72          914.48
Permanent Ineff=
       F       F
Bank Sta=298.8,318.82
XS Rating Curve= 0 ,0
Exp/Cntr(USF)=0,0
Exp/Cntr=0.3,0.1

Type RM Length L Ch R = 1 ,10007   ,489,500,509.4
XS GIS Cut Line= 6
1639795.73963343421956.9864365011639759.99954742422043.656538755
1639659.92592867422286.3322345021639631.33346617422355.668053836
1639597.97592135422436.5599524231639562.23583534422523.230054677
#Sta/Elev= 30
       0 1037.83    17.7 1025.61    34.1 1016.37    42.8 1012.14    57.6    1008
      86  986.16   102.9   976.1   117.7  969.77   146.4  951.39   177.1  941.95
   187.9  936.42   207.2  921.53   213.8  917.66   233.2  908.26   267.8  896.87
   272.1  893.59   280.8  883.77   296.5  875.53   306.7   874.8  315.89875.5927
     324  878.93   327.2  879.06   436.5  879.11   475.5  881.47   502.6   889.6
     536  896.09   556.9  905.04   570.6  908.12   596.6  922.07   612.5  935.49
#Mann= 5 ,-1,0
       0      .1       0  266.25     .06       0   296.5    .045       0
  315.89     .06       0  431.25      .1       0
Bank Sta=296.5,315.89
XS Rating Curve= 0 ,0
Exp/Cntr(USF)=0,0
Exp/Cntr=0.3,0.1

Type RM Length L Ch R = 1 ,9507    ,507.6,500,490.9
XS GIS Cut Line= 6
1639536.12696368421879.0026685891639455.96800326421953.900484666
1639371.88122918  422007.36822551639299.07133542 422036.12702626
1639042.75787167422093.0107707531638957.42634942 422137.06908159
#Sta/Elev= 30
       0  991.68    51.7  977.32    66.7  971.98    82.1   964.4   101.8  950.87
   128.5  943.34   140.5   938.2   149.2  933.03   160.8  922.36   166.4  919.14
   185.4  911.58   207.1  900.69   230.6  894.96   237.8  892.18   247.8  886.79
   260.7  877.81   269.3  873.45   277.9  871.78     315   871.1   327.2  868.24
   338.6  867.54   347.6   868.1   355.7  872.26   359.8  872.64   396.4  871.36
   412.6  871.95   465.6  871.25   580.5  873.56   605.6  876.22   646.6  885.87
#Mann= 8 ,-1,0
       0      .1       0  287.63     .06       0   327.2    .045       0
   347.6     .06       0  387.63     .07       0  427.63      .1       0
  492.64     .05       0  590.54      .1       0
Bank Sta=327.2,347.6
XS Rating Curve= 0 ,0
Exp/Cntr(USF)=0,0
Exp/Cntr=0.3,0.1

Type RM Length L Ch R = 1 ,9007    ,496.1,500,503.1
XS GIS Cut Line= 6
1639074.94448709 421449.206612171639027.93572284421530.319638923
1638896.31229842421757.4349983331638858.70607442421822.325616583
1638814.83116217421898.0301895891638767.82272601421979.142888263
#Sta/Elev= 30
       0 1006.88    22.3   995.9    36.7   990.7    68.6  974.88    86.5   969.5
   117.3  958.39   137.9  948.39   159.6  942.79   173.2  937.91     198  919.06
   203.5  915.68   229.9  906.02   248.9  897.29   253.3  893.52   260.9  883.54
   273.8  873.48   279.6  870.39   290.5  867.73   299.7   861.1     306  860.57
   314.8   861.2   323.5  863.89   359.8  866.27   452.2     867   496.2  868.59
   521.6  870.64   544.8  875.47   563.5  883.94   601.6  890.49   612.5  894.11
#Mann= 6 ,-1,0
       0      .1       0  251.25     .06       0   299.7    .045       0
   314.8     .06       0  366.25     .05       0  528.75      .1       0
Bank Sta=299.7,314.8
XS Rating Curve= 0 ,0
Exp/Cntr(USF)=0,0
Exp/Cntr=0.3,0.1

Type RM Length L Ch R = 1 ,8507    ,502,500,497.5
XS GIS Cut Line= 6
1638754.84243701421202.7687848361638687.13522334421275.525201008
1638624.26887925421340.9391121721638568.36643201421393.186054915
1638485.74323767421449.5189475121638274.02187634421593.872661427
#Sta/Elev= 30
       0 1005.73    11.7  999.23    20.2  992.61    27.5   985.6    31.5  982.95
      51  974.13    79.6  963.62    92.1  957.18   107.9  947.16   144.2  934.37
   153.2   929.3   172.9  914.83   195.4  908.22   209.7  900.23   223.9  894.98
   242.2  879.66   259.8  867.86   269.2  862.48   283.6  858.64   300.8   858.7
   308.1  855.45   315.3  854.53   323.9  855.52   341.2  860.09   354.1  860.86
   421.9  860.97   450.6   862.2   499.8  866.93   577.9  871.75   622.9  876.41
#Mann= 7 ,-1,0
       0      .1       0  240.11     .06       0   308.1    .045       0
   323.9     .06       0  406.63     .05       0  569.13     .08       0
  579.13     .05       0
Bank Sta=308.1,323.9
XS Rating Curve= 0 ,0
Exp/Cntr(USF)=0,0
Exp/Cntr=0.3,0.1

Type RM Length L Ch R = 1 ,8007    ,501.1,500,499.2
XS GIS Cut Line= 6
  1638448.803679420786.1337913421638278.68197201420977.765625924
1638212.29332526421052.5489409271638162.50143009421108.636427179
1638104.41165125421174.0716637521638042.17194635421244.180775508
#Sta/Elev= 30
       0  994.03    10.7  986.34    30.5  974.51      46  970.41    64.5  963.75
    94.1  946.55   120.9  938.71   131.6  934.34   152.4     920   163.7  913.93
   169.7  911.39   190.4   905.4   205.9  898.15   217.9  893.71     224  890.47
   234.5  879.09     243  872.38   260.1  861.62   270.7  857.36   286.7  855.04
   297.4  849.71   308.1  848.94  315.75849.6883   332.4  852.79   420.4  856.01
   458.9  859.67   500.7  867.39     522  872.66   548.8  877.25   612.5   890.2
#Mann= 5 ,-1,0
       0      .1       0  256.25     .06       0   297.4    .045       0
  315.75     .06       0  396.25     .05       0
Bank Sta=297.4,315.75
XS Rating Curve= 0 ,0
Exp/Cntr(USF)=0,0
Exp/Cntr=0.3,0.1

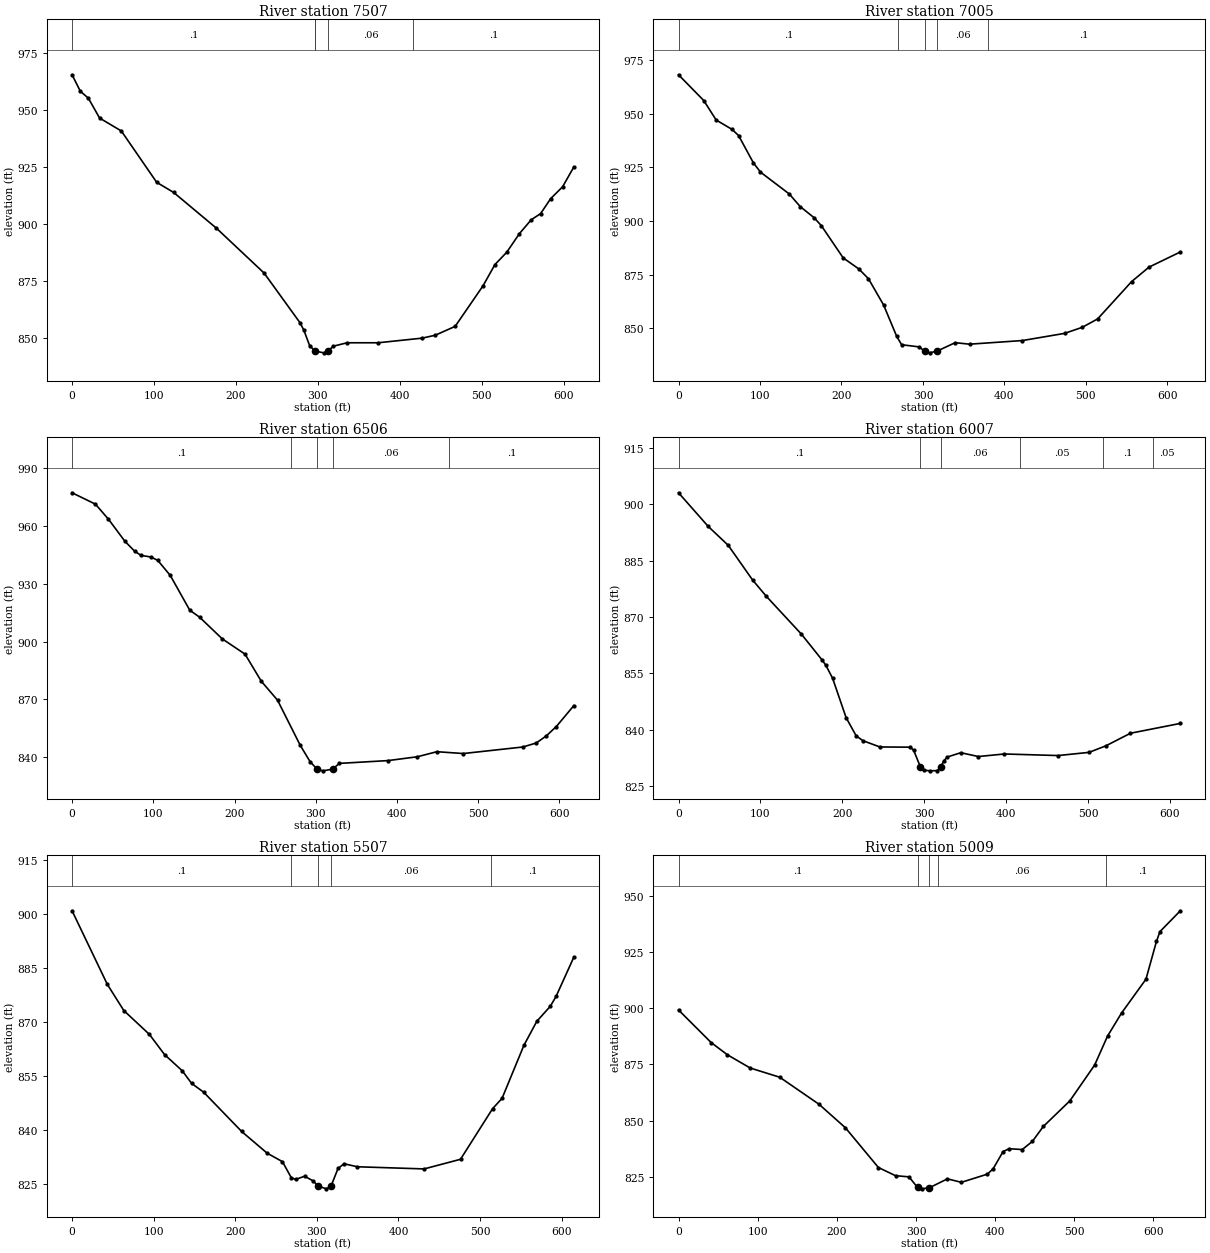
Type RM Length L Ch R = 1 ,7507    ,496.7,501.9,505.1
XS GIS Cut Line= 6
1638039.61027168420440.2709660081637985.24194209420516.659920841
1637893.08792692   420650.5028291637836.37741043420732.867165595
1637744.22405143420866.7104018331637691.05781917420943.927110925
#Sta/Elev= 30
       0  965.44    10.1  958.22    19.9  955.17    33.6  946.47    60.1  940.82
   103.3   918.3     124  913.86   176.2  898.19   234.4  878.53   278.2  856.77
     283  853.43   290.1   846.6  296.81844.3172   307.3  843.56   312.2   844.3
   318.8  846.46   335.6  847.97   373.5  847.97   427.3     850   443.3  851.28
   467.6  855.16   501.6  872.93   516.1  882.22   530.7  887.71     546  895.79
   560.4  901.87   571.9  904.58   584.1  911.12   598.7  916.32   612.5  925.04
#Mann= 5 ,-1,0
       0      .1       0  296.26     .06       0  296.81    .045       0
   312.2     .06       0  416.26      .1       0
Bank Sta=296.81,312.2
XS Rating Curve= 0 ,0
Exp/Cntr(USF)=0,0
Exp/Cntr=0.3,0.1

Type RM Length L Ch R = 1 ,7005    ,495.4,499.3,501.1
XS GIS Cut Line= 6
1637872.69984435420164.5257825851637785.13932392420201.658254251
 1637704.2464411 420238.389480011637637.10582735420273.148924917
1637545.88127226 420314.287294091637308.47459485420410.734935835
#Sta/Elev= 30
       0  968.05      31  956.04    46.2  946.98    65.8   942.6    73.7  939.75
    91.9  927.03   100.6  922.73   135.8   912.6   149.4  906.67   166.5  901.48
   175.3   897.8   202.1   882.8   221.3  877.65   233.1  873.12   251.7  860.88
   267.8  846.25   273.8  842.38   295.7  841.35   302.2  839.26   308.2   838.6
   317.3  839.41   339.6  843.33   357.2  842.63     422  844.32   473.8  847.66
   495.4  850.46   514.4  854.39   556.1  871.76   577.4  878.49   615.9  885.56
#Mann= 5 ,-1,0
       0      .1       0  269.56     .06       0   302.2    .045       0
   317.3     .06       0  379.63      .1       0
Bank Sta=302.2,317.3
XS Rating Curve= 0 ,0
Exp/Cntr(USF)=0,0
Exp/Cntr=0.3,0.1

Type RM Length L Ch R = 1 ,6506    ,501.6,498.8,495.3
XS GIS Cut Line= 6
1637896.94421843419827.6852489261637713.69228834419824.813535511
1637537.57912351419829.0356399271637462.57894543419827.843057007
1637375.47085193419813.9894101771637283.06749342419791.778496593
#Sta/Elev= 30
       0  977.13    28.8  971.22    44.8  963.43    64.9  952.06    76.9  946.89
    84.9  944.67    96.9  943.84   105.5  942.09   120.9  934.27   144.9  916.24
   156.9  912.66   184.9  901.39   212.9  893.48   232.9  879.44   252.9  869.62
   280.9  846.18   292.9  837.79   301.8  833.76   308.9  832.97   320.9  833.85
   328.9  836.83   388.9  838.28   424.9  840.26   449.1  842.89   481.6  841.94
   554.9  845.33   571.4  847.41   583.7  851.06   596.1  855.93   617.7   866.8
#Mann= 5 ,-1,0
       0      .1       0  269.33     .06       0   301.8    .045       0
   320.9     .06       0  464.46      .1       0
Bank Sta=301.8,320.9
XS Rating Curve= 0 ,0
Exp/Cntr(USF)=0,0
Exp/Cntr=0.3,0.1

Type RM Length L Ch R = 1 ,6007    ,504.2,500,493.4
XS GIS Cut Line= 6
1637935.47366892419268.9521144181637843.69432493419288.206340998
1637758.73058408419309.1216535121637588.80310242419350.950638086
1637431.01371984419389.7924239191637339.91875768419412.044676006
#Sta/Elev= 30
       0   903.1    36.1  894.17    60.7   889.1    90.3   879.9   106.9   875.6
   149.9  865.48   175.7  858.45   179.9  857.14   188.1   853.7   204.6   843.2
   216.9  838.36   225.2  837.07   245.8  835.41   282.8  835.35     287  834.55
   295.2  830.13   299.3  829.22   307.6  829.05   315.8  829.11   319.9  830.06
     324  831.75   328.2  832.74   344.6  833.88     366  832.86   397.8  833.54
   463.3  833.12   501.2  833.97   521.8  835.72   551.7  839.06   612.6  841.68
#Mann= 6 ,-1,0
       0      .1       0   295.2    .045       0   319.9     .06       0
  416.28     .05       0  518.78      .1       0  578.78     .05       0
Bank Sta=295.2,319.9
XS Rating Curve= 0 ,0
Exp/Cntr(USF)=0,0
Exp/Cntr=0.3,0.1

Type RM Length L Ch R = 1 ,5507    ,494.3,498.1,501.5
XS GIS Cut Line= 6
1637644.55069435418695.4489963351637595.90249768418777.140762091
1637547.62503517418851.3427134161637499.54671925418908.969894752
1637432.74173476418983.3818194271637261.53669658 419174.04613626
#Sta/Elev= 30
       0  900.97    43.2   880.5    63.4  873.22    94.7   866.6   113.4  860.95
     135  856.47   146.5  852.95   161.2  850.51   207.8  839.58     239  833.55
   257.8  831.18   268.8  826.65   274.2  826.26     285  827.13   295.7  825.79
   301.1  824.44   311.7  823.62   317.4   824.4   325.9  829.29   333.3   830.6
   349.5  829.76   431.4  829.16     476  831.84   515.3  845.92   526.9  848.79
   553.7  863.54   569.5  870.23     586  874.39   593.1  877.15   614.9  888.08
#Mann= 5 ,-1,0
       0      .1       0  268.65     .06       0   301.1    .045       0
   317.4     .06       0  513.65      .1       0
Bank Sta=301.1,317.4
XS Rating Curve= 0 ,0
Exp/Cntr(USF)=0,0
Exp/Cntr=0.3,0.1

Type RM Length L Ch R = 1 ,5009    ,507.1,507.3,501.6
XS GIS Cut Line= 6
  1637548.100756418447.7785599231637371.53975743418492.498942927
1637299.21149001418514.2308548391637205.88326459418551.320347592
1637132.81221651 418569.740586341636948.87918542418649.073761001
#Sta/Elev= 30
       0  899.21    41.2  884.72    61.8  879.27    90.6  873.39   127.8  869.31
   177.4   857.3   210.8  846.83   252.5  829.15   274.1  825.52   291.1     825
   301.9  820.31   307.2  819.67     317  820.17   339.7  824.11   357.3  822.57
   390.2  826.21   397.5  828.62     410  836.26   417.7  837.51   434.2  837.15
   447.1   840.8   460.8   847.4   494.3  858.78   525.7  874.74   541.9  887.56
   559.6  897.82   590.5   912.9   603.8  929.77   608.2  934.07   633.9  943.32
#Mann= 5 ,-1,0
       0      .1       0   301.9    .045       0     317      .1       0
  327.67     .06       0  539.55      .1       0
Bank Sta=301.9,317
XS Rating Curve= 0 ,0
Exp/Cntr(USF)=0,0
Exp/Cntr=0.3,0.1

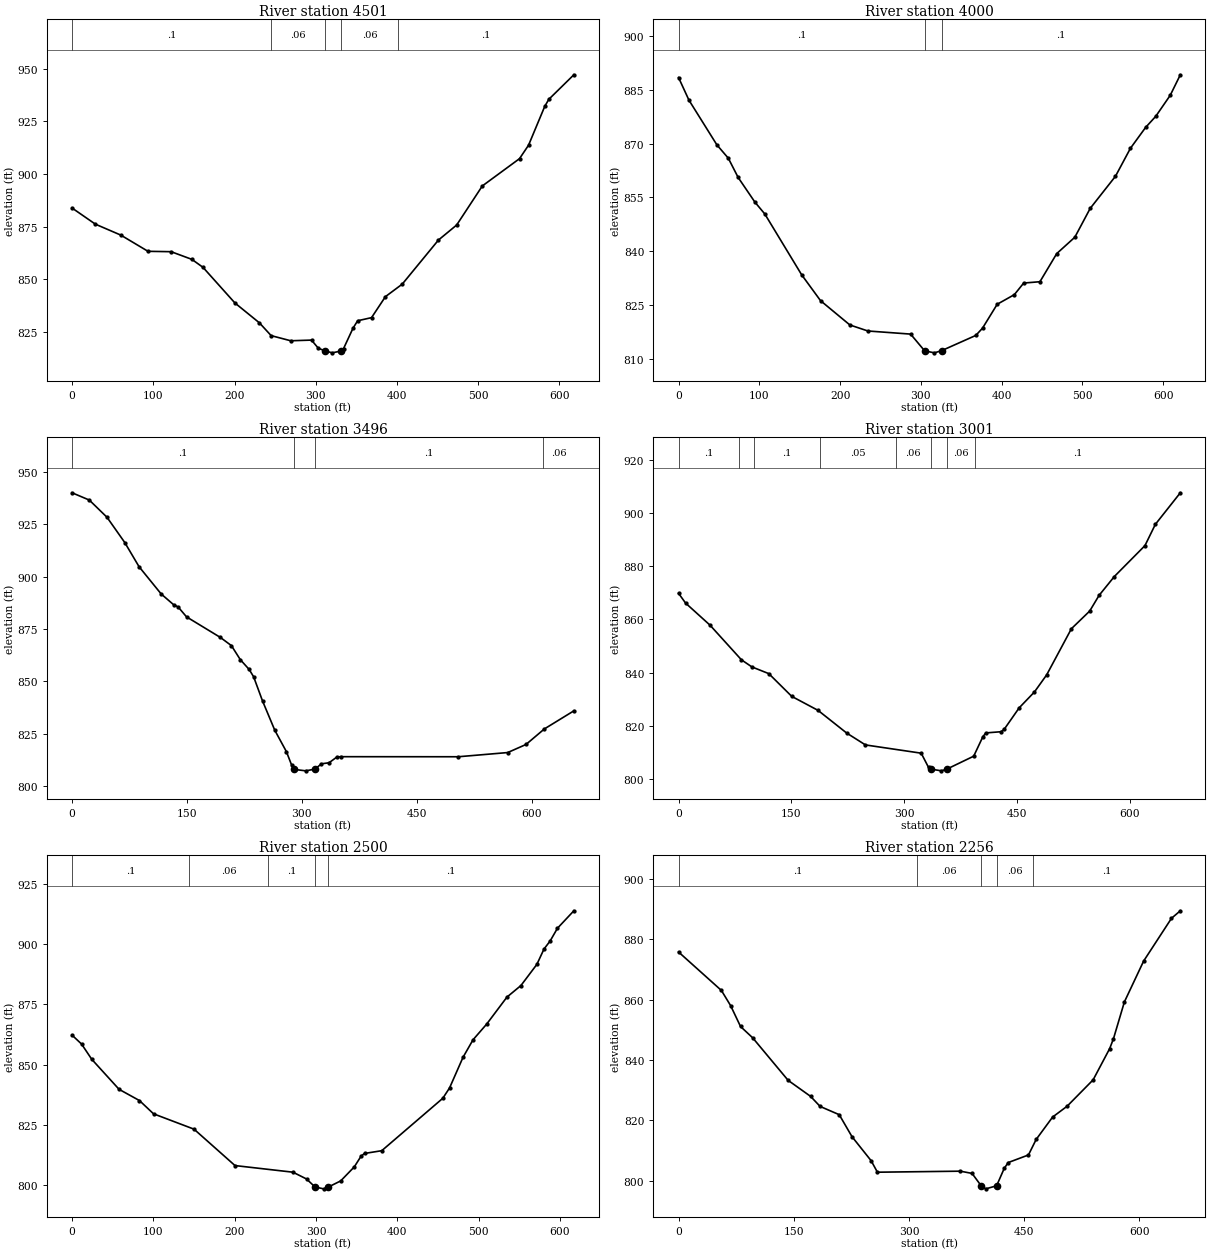
Type RM Length L Ch R = 1 ,4501    ,502,501.3,500.3
XS GIS Cut Line= 6
1637191.17266409417955.0134693381637122.57732885 418021.63767992
 1637059.1233875418084.7497584221637004.34528184 418138.08528167
1636926.92188026418201.3755094261636728.20935117418363.101563916
#Sta/Elev= 30
       0  883.82    28.7  876.16      60  870.97    93.5  863.27     122  863.09
   147.5  859.45   161.2  855.66   200.5  838.75   230.7   829.3   245.1  823.25
   269.2  820.81   294.8  821.13   303.2  817.25   311.8  815.98   320.3  815.08
   331.7  815.99   334.2  817.06   345.9  826.78   351.6  830.31   368.7  831.79
   385.8  841.75   406.5  847.69   451.1  868.63   473.5  875.75   505.1   894.3
   550.9  907.26     562  913.63     582  932.11     587  935.43   617.8  947.07
#Mann= 5 ,-1,0
       0      .1       0  245.12     .06       0   311.8    .045       0
   331.7     .06       0  401.58      .1       0
Bank Sta=311.8,331.7
XS Rating Curve= 0 ,0
Exp/Cntr(USF)=0,0
Exp/Cntr=0.3,0.1

Type RM Length L Ch R = 1 ,4000    ,498.7,503.9,501.1
XS GIS Cut Line= 6
1636916.49440767417577.746507332 1636832.3052716417629.727046415
1636760.70666151417684.713485003  1636634.236442417805.669607922
1636584.89697376417862.442788333 1636468.6914975418002.158060089
#Sta/Elev= 30
       0  888.49    12.9  882.16    47.5  869.68    61.6  865.97    73.8  860.59
    94.5  853.72   106.8   850.4   152.4  833.43   175.8   826.2   212.1  819.42
   234.4  817.74   287.3  816.87   304.7  812.19   316.8  811.64  325.83812.2639
     368   816.5   376.3  818.52   394.5   825.2   415.7  827.88   427.3  831.12
   447.4  831.49   468.2  839.34   490.6  843.91   509.6  851.95   540.9  860.92
   559.4  868.72   578.2  874.55   590.8  877.66   608.7  883.52   621.2  889.25
#Mann= 3 ,-1,0
       0      .1       0   304.7    .045       0  325.83      .1       0
Bank Sta=304.7,325.83
XS Rating Curve= 0 ,0
Exp/Cntr(USF)=0,0
Exp/Cntr=0.3,0.1

Type RM Length L Ch R = 1 ,3496    ,485.1,495.1,506.6
XS GIS Cut Line= 6
1636760.43402426417145.1210602521636574.80578659417321.702399999
1636491.89584742417386.0408540071636421.35300951 417435.02730459
1636343.61399175417495.439585343 1636252.0544636417556.009018004
#Sta/Elev= 30
       0   939.9    22.5  936.43    45.6  928.24    68.8  916.21    87.5  904.67
   116.4  891.68   132.6  886.58   138.5   885.5   149.5  880.78   193.7  870.98
   208.1  867.08   219.7  860.41   231.3  855.72   237.1  852.24   248.7  840.75
   264.7   826.8   279.9  816.58   286.9  810.01     290  808.12   305.2  807.43
   317.2  808.26   325.7  810.78   335.6  811.28   345.6  813.96   350.7  814.17
   504.3  814.14   568.9  816.14   592.8  819.99   616.8   827.4   655.3  836.01
#Mann= 4 ,-1,0
       0      .1       0     290    .045       0   317.2      .1       0
  615.48     .06       0
Bank Sta=290,317.2
XS Rating Curve= 0 ,0
Exp/Cntr(USF)=0,0
Exp/Cntr=0.3,0.1

Type RM Length L Ch R = 1 ,3001    ,504.4,501,486.8
XS GIS Cut Line= 6
1636512.24849701416994.3559418321636419.30905034417048.832210839
1636326.90864459417089.3081797511636243.59417868417109.608664095
1636150.24167509417073.626452595  1635881.993852417121.355687842
#Sta/Elev= 30
       0  869.83     9.4  866.15    41.9  857.84    83.6  844.83    97.5  842.16
     120  839.63   150.5  831.08   185.5  825.81   223.5   817.3   248.5  812.82
   322.6  809.72   332.4  804.35     335  803.75   349.5  803.08   356.7  803.73
   392.4  808.59   404.6  815.91   408.6  817.34   428.8  817.79   432.8  818.64
   452.9  826.78   473.1  832.72   489.4  839.16   522.3  856.52   546.6  863.15
   559.1  869.06   579.4  876.15   620.1  887.77   633.9  895.76   667.1  907.63
#Mann= 8 ,-1,0
       0      .1       0      80     .05       0     100      .1       0
  187.73     .05       0  288.61     .06       0     335    .045       0
   356.7     .06       0  394.36      .1       0
Bank Sta=335,356.7
XS Rating Curve= 0 ,0
Exp/Cntr(USF)=0,0
Exp/Cntr=0.3,0.1

Type RM Length L Ch R = 1 ,2500    ,249.4,244,239.2
BEGIN DESCRIPTION:
Structure 3 XS 4
END DESCRIPTION:
XS GIS Cut Line= 6
1636383.23169467416577.9407641741636138.80764285416654.888116837
1636043.42233492416684.9159439211635971.97858018416707.738732919
1635885.86884426416731.7413095831635792.64593358416756.856088758
#Sta/Elev= 30
       0  862.27    11.7  858.56    24.2  852.25    57.8  839.78    82.9  835.11
   100.2  829.61     150  823.24   200.4  808.13   271.7  805.38   288.4  802.56
  298.83 799.245   309.4  798.47     315  799.19   330.4  801.76   347.1  807.58
   355.5  812.04   359.7  813.16   380.9   814.3     456  836.06   464.3  840.35
   480.9  853.09   493.2  860.35     510  866.87   534.9  878.06   552.1  882.86
   571.7  891.64   580.5  898.03     588  901.34     597  906.63   617.2  913.89
#Mann= 5 ,-1,0
       0      .1       0  143.75     .06       0  241.25      .1       0
  298.83    .045       0     315      .1       0
Bank Sta=298.83,315
XS Rating Curve= 0 ,0
Exp/Cntr(USF)=0,0
Exp/Cntr=0.3,0.1

Type RM Length L Ch R = 1 ,2256    ,38.5,39.8,40.7
BEGIN DESCRIPTION:
Structure 3 XS 3
END DESCRIPTION:
XS GIS Cut Line= 5
1636353.93434907416291.1568682061636052.73993586416373.300799082
1636022.03967887416418.9363162351635978.89337174416467.061043414
1635802.98919653416601.478384847
#Sta/Elev= 30
       0   875.8    55.8  863.06    67.8  858.03    80.7  851.12    96.5  847.37
   142.7  833.27   171.9  827.97   184.3  824.64   209.2   821.9   225.8  814.62
   250.7  806.66   258.9  802.85   366.9  803.19   382.1  802.45     394  798.33
     400  797.34  414.04  798.35     424  804.14   429.2  806.05   455.5  808.56
   465.5  813.69     487  821.13   505.8   824.7   539.7  833.45   561.2  843.78
   566.2  847.09   580.4  859.27   605.5  872.82   641.7  886.96   653.2  889.45
#Mann= 5 ,-1,0
       0      .1       0     310     .06       0     394    .045       0
  414.04     .06       0  461.83      .1       0
Bank Sta=394,414.04
XS Rating Curve= 0 ,0
Exp/Cntr(USF)=0,0
Exp/Cntr=0.3,0.1

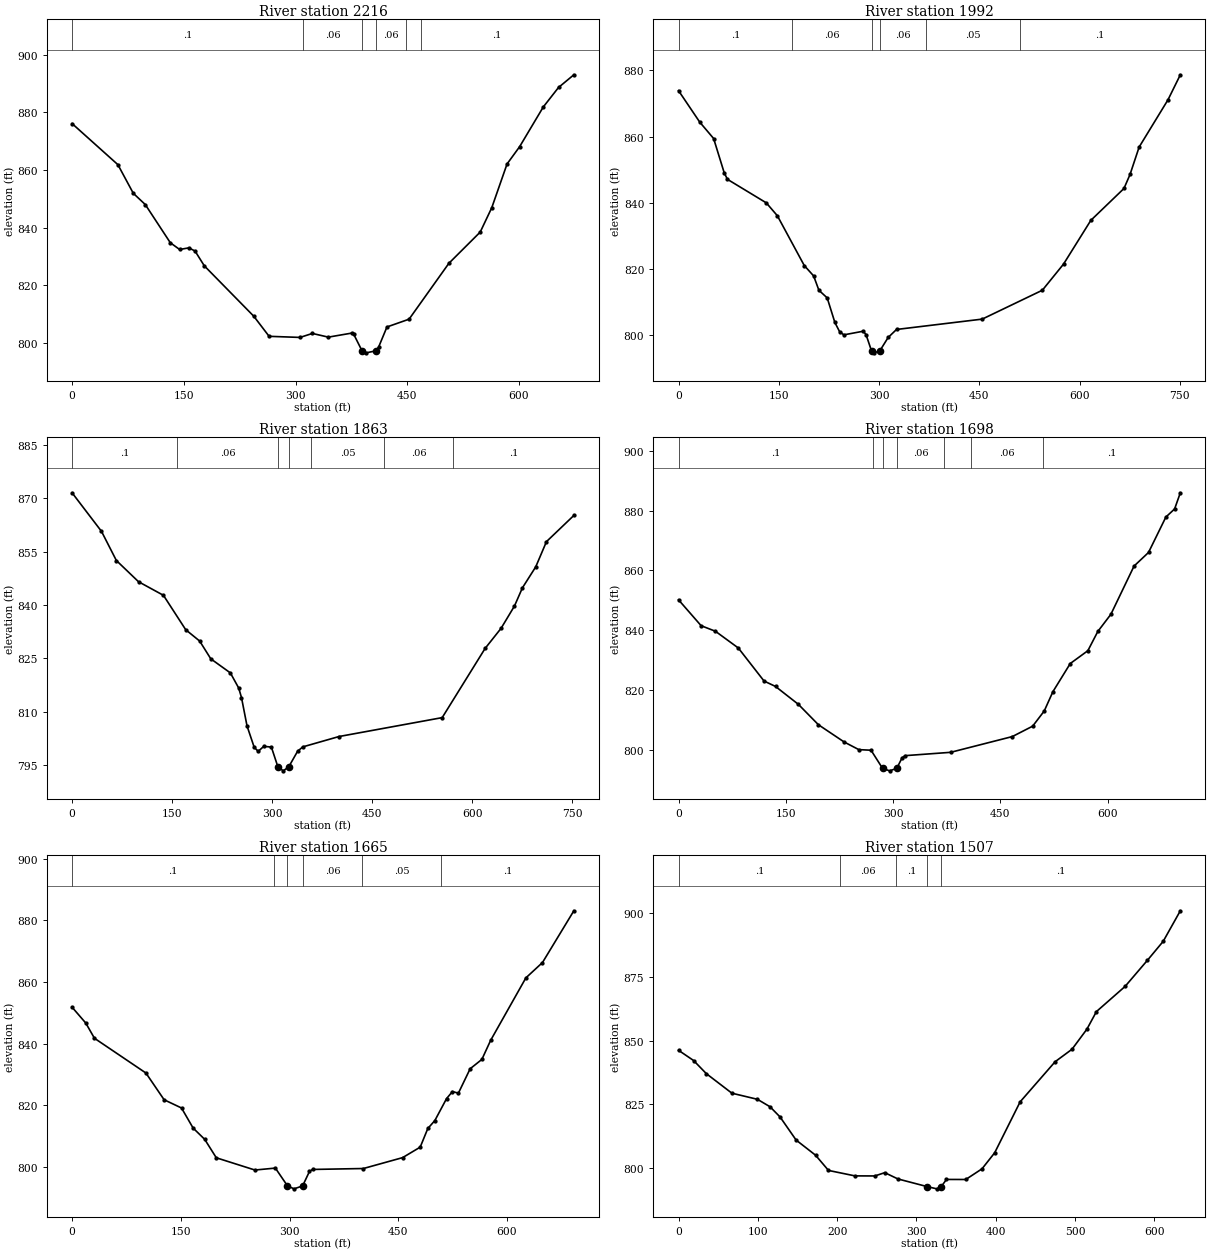
Type RM Length L Ch R = 1 ,2216    ,217.1,223.8,226.8
BEGIN DESCRIPTION:
Structure 3 XS 2
END DESCRIPTION:
XS GIS Cut Line= 5
1636351.44513905416271.243187994 1636024.5288889416360.025012274
1636006.27468203416391.5550059431635968.10679496416428.063419665
1635766.48078281416568.288917826
#Sta/Elev= 30
       0  876.09    61.5  861.83    82.2  851.89    98.3  847.98   131.9  834.73
   144.4  832.39   156.8  832.96   165.1  831.85   177.5  826.73   243.9  809.24
   264.5  802.26     306  801.88   322.6  803.26     344  801.98   375.2  803.37
   378.2  802.92   389.3   797.2   394.8  796.53  407.51 797.203   411.4  798.46
   422.7  805.51   452.4  808.21   505.9  827.62   547.9  838.44   563.4  846.89
   583.9  862.06   600.8  868.07   632.6  881.87     653  888.61   673.6  893.02
#Mann= 6 ,-1,0
       0      .1       0     310     .06       0   389.3    .045       0
  407.51     .06       0  448.01     .05       0  468.01      .1       0
Bank Sta=389.3,407.51
XS Rating Curve= 0 ,0
Exp/Cntr(USF)=0,0
Exp/Cntr=0.3,0.1

Type RM Length L Ch R = 1 ,1992    ,129.7,129.5,129.1
BEGIN DESCRIPTION:
Structure 3 XS 1
END DESCRIPTION:
XS GIS Cut Line= 3
1636310.78804195416115.2526929991635895.08996752416228.096880868
1635745.73736592416511.037087216
#Sta/Elev= 30
       0  873.87    31.8  864.33    52.5  859.39    68.4  848.98    73.2  847.04
   131.3  839.93   147.8  836.04   188.1  820.97   202.1  817.83     210  813.49
   222.4  811.18   233.9  803.74   240.9  800.98   247.3     800   276.3   801.1
   280.5  800.08   288.8   795.1   292.9  794.56   301.2  795.18   313.6  799.21
   326.1  801.63   454.3  804.76   544.3   813.5     576  821.41   616.8  834.63
   666.4  844.28   675.5  848.54   689.1  856.82   732.3  871.12   750.7  878.67
#Mann= 6 ,-1,0
       0      .1       0     170     .06       0   288.8    .045       0
   301.2     .06       0     370     .05       0  510.74      .1       0
Bank Sta=288.8,301.2
XS Rating Curve= 0 ,0
Exp/Cntr(USF)=0,0
Exp/Cntr=0.3,0.1

Type RM Length L Ch R = 1 ,1863    ,165.3,164.6,163.6
BEGIN DESCRIPTION:
Structure 2 XS 4
END DESCRIPTION:
XS GIS Cut Line= 4
1636300.10897035415978.2884207211636176.70876752416012.194855095
1635762.33209943416137.6555832371635570.99804003416134.548426975
#Sta/Elev= 30
       0  871.48    44.1  860.66    66.4  852.48    99.6  846.53     137  842.71
   170.4  833.06   191.3  829.88     208  824.89   237.3  820.95   249.8  816.71
     254  814.04   262.3  806.07   273.1  800.05   279.1  798.94   287.4  800.34
   298.8  800.14   308.6  794.58   316.7  793.47     325  794.64   338.1  798.96
   345.9  800.19   400.3   803.1   554.9   808.4   619.2   827.8   643.2  833.46
   663.2  839.69   675.2  844.82   695.2  850.72   711.2  857.77   752.3  865.12
#Mann= 7 ,-1,0
       0      .1       0  157.97     .06       0   308.6    .045       0
     325     .06       0  357.97     .05       0  467.97     .06       0
  570.93      .1       0
Bank Sta=308.6,325
XS Rating Curve= 0 ,0
Exp/Cntr(USF)=0,0
Exp/Cntr=0.3,0.1

Type RM Length L Ch R = 1 ,1698    ,33.6,33.7,34.2
BEGIN DESCRIPTION:
Structure 2 XS 3
END DESCRIPTION:
XS GIS Cut Line= 6
1636223.66569102415899.5211573661635982.21231844415896.202210664
1635962.29863823415902.8401040681635895.08996752415931.051151036
1635866.87892055415988.3029816461635568.17371737415940.178254466
#Sta/Elev= 30
       0   850.2    31.6  841.56    51.6  839.71    83.6  834.12   119.6  823.09
   135.6  821.29   167.6  815.31   195.6  808.51   231.6  802.75   252.1   800.2
   269.2     800  285.27  793.96   295.2  793.12   305.2  793.96   312.6  797.46
   316.9  798.19   380.5   799.3   466.8  804.56   495.2  808.03   511.4   813.1
   523.5  819.53   547.8  828.94   572.4  833.22   586.3  839.63   604.6  845.37
     637  861.47   657.2     866   681.5  877.83   693.7  880.53   701.7  885.93
#Mann= 7 ,-1,0
       0      .1       0  272.47     .06       0  285.27    .045       0
   305.2     .06       0  371.33     .05       0  409.18     .06       0
  509.18      .1       0
Bank Sta=285.27,305.2
XS Rating Curve= 0 ,0
Exp/Cntr(USF)=0,0
Exp/Cntr=0.3,0.1

Type RM Length L Ch R = 1 ,1665    ,151.7,158,162.2
BEGIN DESCRIPTION:
Structure 2 XS 2
END DESCRIPTION:
XS GIS Cut Line= 6
1636226.98463772415875.4587937771635968.93653164415865.501953671
1635887.62233744415896.2022106641635874.34655063415903.669840744
1635844.47603031 415954.283777951635574.81161077415911.137470823
#Sta/Elev= 30
       0  851.85    18.9  846.71    30.9  841.77   101.9   830.5     127  821.83
     151  819.16     167  812.65     183  808.99     199  803.01   252.3  799.04
   280.5  799.67  297.14  793.92   306.2  792.94  318.06  793.88   327.5  798.57
   331.8  799.23   401.9  799.53     456  803.06   480.3  806.46   490.8  812.51
   500.5  815.08   516.7  822.22   524.8  824.49     533  823.97   549.2  831.88
   565.4  834.92   577.5   841.1   626.1  861.36     649  866.33   692.3  883.12
#Mann= 6 ,-1,0
       0      .1       0  278.24     .06       0  297.14    .045       0
  318.06     .06       0  400.39     .05       0  509.16      .1       0
Bank Sta=297.14,318.06
XS Rating Curve= 0 ,0
Exp/Cntr(USF)=0,0
Exp/Cntr=0.3,0.1

Type RM Length L Ch R = 1 ,1507    ,508.3,506.6,503.8
BEGIN DESCRIPTION:
Structure 2 XS 1
END DESCRIPTION:
XS GIS Cut Line= 6
1636219.00859793415789.782891676 1636119.4759886415779.130025834
1636027.06738076415761.222253263  1635949.584268415737.558586672
1635850.27934851415717.733823165 1635594.5971171415700.689237833
#Sta/Elev= 30
       0  846.23      19  842.21    35.1  837.05    67.3  829.38    99.5  826.98
   115.4  824.05     128  820.06   148.3  810.97   172.8  805.03   189.1  799.05
   222.4  796.91   247.5  796.88   260.1  798.17   276.7   795.7   313.5   792.7
   325.7  791.82  331.03 792.602   337.9  795.51   362.2  795.49   382.7  799.68
   398.7  805.99   430.8  825.99   474.9  841.74   496.2  846.64     515  854.53
     527  861.43   563.1   871.3   591.1   881.5   611.2  889.02   632.8  901.02
#Mann= 5 ,-1,0
       0      .1       0  204.23     .06       0  274.23      .1       0
   313.5    .045       0  331.03      .1       0
Bank Sta=313.5,331.03
XS Rating Curve= 0 ,0
Exp/Cntr(USF)=0,0
Exp/Cntr=0.3,0.1