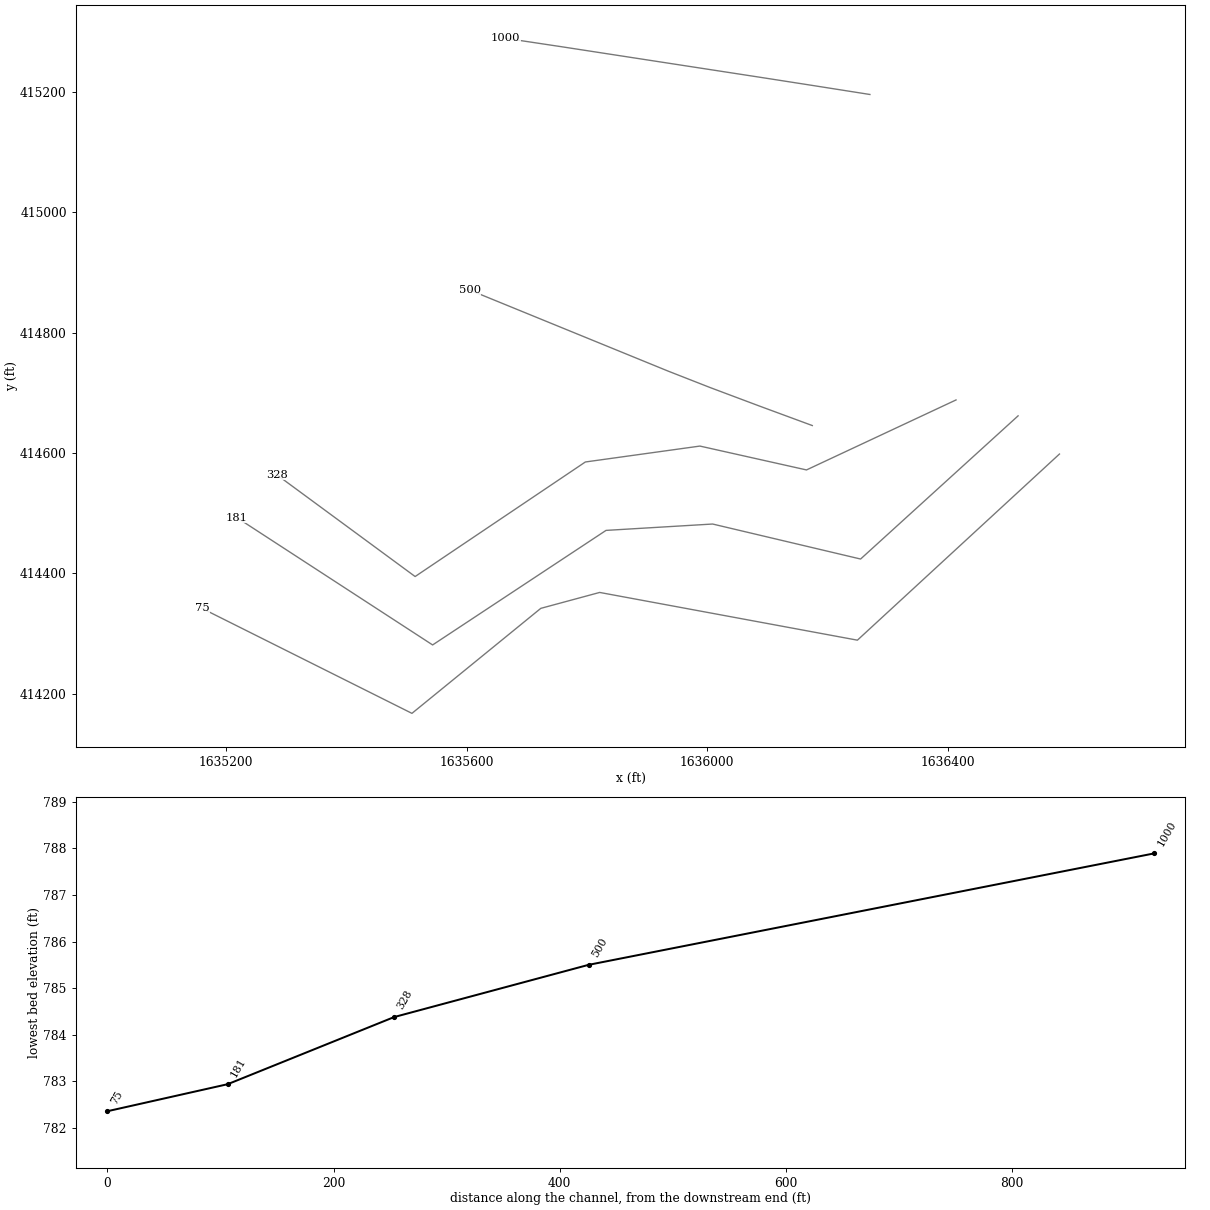
HEC-RAS study RUSHRN1.prj: RUSHRN1

--- RUSHRN1.g01 (geometry) --- (continued)

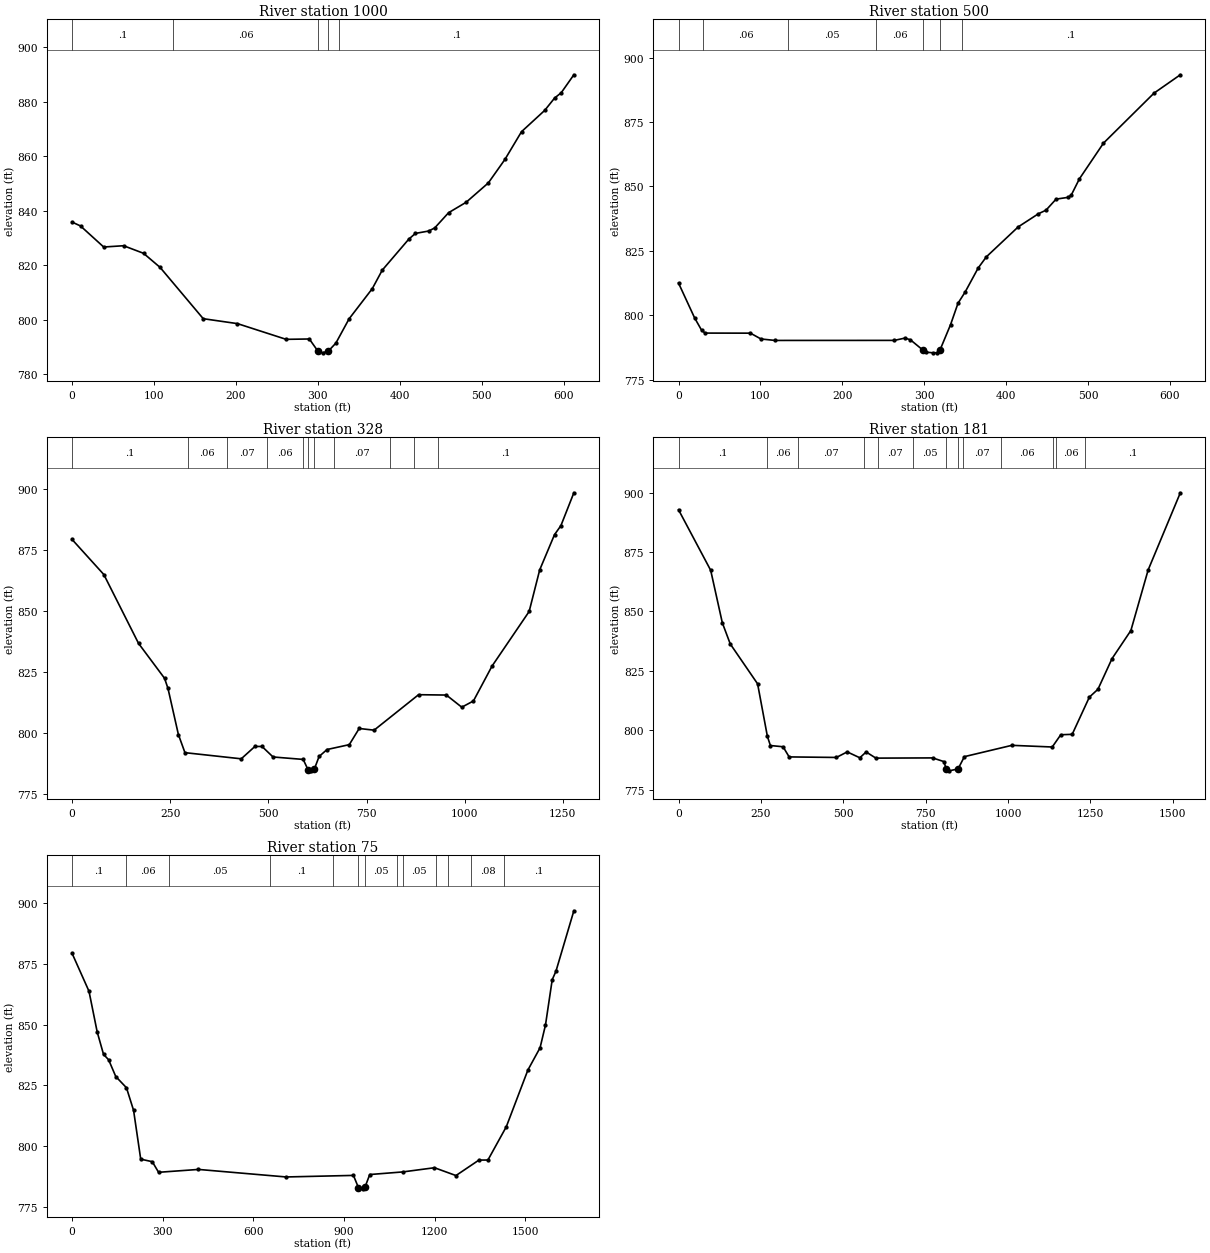
Type RM Length L Ch R = 1 ,1000    ,501.7,500,496.4
XS GIS Cut Line= 6
1636270.25029334415196.0468744191636177.64089851415210.632475168
1636091.18503468415224.1107946781636017.05723017415235.514315173
1635757.60991442415275.4295896741635664.90078226 415289.36591351
#Sta/Elev= 30
       0  835.83    10.3  834.41    38.6  826.69    62.9  827.16    87.2  824.39
   107.4  819.23   160.1  800.41   201.9   798.6   261.3  792.84   289.6  792.97
   300.1  788.51   305.8  787.89  312.85788.5472     322  791.45   338.1  800.34
   366.5  811.45   378.6   818.2     411  829.57   419.1  831.68   435.3  832.55
   442.7   833.7   459.6  839.27     481  843.09   508.1  850.19   528.4  858.82
   548.6  868.97   576.9  876.78     589  881.31   597.1  883.26   612.5  889.84
#Mann= 5 ,-1,0
       0      .1       0  123.75     .06       0   300.1    .045       0
  312.85     .06       0  326.25      .1       0
Bank Sta=300.1,312.85
XS Rating Curve= 0 ,0
Exp/Cntr(USF)=0,0
Exp/Cntr=0.3,0.1

Type RM Length L Ch R = 1 ,500     ,167.6,171.9,176.8
BEGIN DESCRIPTION:
Structure 1 XS 4
END DESCRIPTION:
XS GIS Cut Line= 6
1636174.49818826414645.8366887571636086.48688135414678.294957176
1636004.53133659414709.0504730941635934.68764426414736.400484011
1635691.67697543414835.6578314161635604.88745084414871.106579423
#Sta/Elev= 30
       0  812.54    19.6  799.06    28.1   794.3    32.4  793.16    87.8  793.13
   100.6  790.88   117.7  790.31   263.5  790.33   276.4  791.22     283  790.57
     298  786.66   302.3  785.76     311   785.5   315.3  785.55  319.27786.6487
   332.1  796.43   341.2  804.74   349.9  809.08   365.8  818.39   375.8  822.72
   414.7  834.34   439.4  839.43   448.6  840.81   460.9  845.09   475.2  845.77
   479.3  846.57   489.4  852.96   518.8  866.81   580.5   886.2   612.6  893.31
#Mann= 7 ,-1,0
       0      .1       0      30     .06       0  133.81     .05       0
  241.34     .06       0     298    .045       0  319.27     .06       0
  346.35      .1       0
Bank Sta=298,319.27
XS Rating Curve= 0 ,0
Exp/Cntr(USF)=0,0
Exp/Cntr=0.3,0.1

Type RM Length L Ch R = 1 ,328     ,136,147.2,149.5
BEGIN DESCRIPTION:
Structure 1 XS 3
END DESCRIPTION:
XS GIS Cut Line= 6
1636413.39112636414688.4046349451636164.84869831414572.065626074
1635987.69611662414611.7266518261635797.32319302414585.285967991
1635514.40787599414394.9130443841635284.37392663414564.133420924
#Sta/Elev= 30
       0  879.22    80.9  864.84   169.3  836.62   235.5  822.32   244.3  818.17
   270.8  799.27   287.5  791.83   430.9  789.31   465.7  794.37   483.8  794.37
   511.9  790.06   588.7  789.06   600.8  784.91   608.9  784.38     617  785.06
   629.2  790.27   649.5  793.12   706.1  795.11   731.3  801.74   769.3  801.05
   882.6  815.59   953.4  815.44   992.6  810.46  1022.3  813.02  1069.7  827.32
  1164.2  849.69  1191.1  866.75  1228.8  881.18  1245.1  884.88  1278.1  898.35
#Mann= 11 ,-1,0
       0      .1       0  294.42     .06       0  394.42     .07       0
  495.96     .06       0  589.11      .1       0   600.8    .045       0
     617      .1       0  668.21     .07       0  808.62     .05       0
  872.17     .06       0  932.17      .1       0
Bank Sta=600.8,617
XS Rating Curve= 0 ,0
Exp/Cntr(USF)=0,0
Exp/Cntr=0.3,0.1

Type RM Length L Ch R = 1 ,181     ,114.9,106.4,106.8
BEGIN DESCRIPTION:
Structure 1 XS 2
END DESCRIPTION:
XS GIS Cut Line= 6
1636516.50979331414661.9639511111636254.74702335414423.997796602
1636008.84866369414482.167301037  1635831.696082414471.591027504
1635543.49262821414281.2181038971635218.27221704414492.743574571
#Sta/Elev= 30
       0  892.77    97.6  867.31   132.9  845.23     157  836.32     240  819.54
   269.7  797.44   278.8  793.59   317.3  793.07   335.7   788.8   479.1  788.57
     512  790.91   550.3  788.43   569.4  790.88     599  788.29   771.3  788.38
   804.8  786.86   813.2  783.65   821.2  782.94  848.39783.7426   867.7  788.91
  1011.8  793.67  1134.3  792.97  1160.2  798.12  1194.9   798.3    1247  813.95
    1273  817.25  1315.7  830.13    1373  841.97  1425.5  867.47  1523.1  899.92
#Mann= 13 ,-1,0
       0      .1       0     270     .06       0  363.76     .07       0
   564.3     .05       0   604.3     .07       0  711.15     .05       0
   813.2    .045       0  848.39     .05       0  864.29     .07       0
  979.06     .06       0 1135.17     .07       0 1145.17     .06       0
 1235.17      .1       0
Bank Sta=813.2,848.39
XS Rating Curve= 0 ,0
Exp/Cntr(USF)=0,0
Exp/Cntr=0.3,0.1

Type RM Length L Ch R = 1 ,75      ,,,
BEGIN DESCRIPTION:
Structure 1 XS 1
END DESCRIPTION:
XS GIS Cut Line= 6
1636585.25557128414598.5063099091636249.45888658414289.150309047
1635821.11980847 414368.472360551635723.28927828414342.031676715
1635509.11973922414167.5231634091635160.10271261414342.031676715
#Sta/Elev= 30
       0  879.32      56  863.71    83.1  846.97   104.1  837.72     121  835.49
   144.6   828.6     180  823.98   203.6  814.65   227.2  794.58   265.5  793.53
   286.3  789.17   418.3  790.35   708.4  787.25   931.2  787.89   947.8  782.85
   964.3  782.36  969.18 782.977   985.2  788.25  1094.2  789.32  1199.4  791.05
  1270.5  787.83  1346.5   794.2  1376.3  794.22  1437.1  807.92  1508.6  831.28
  1548.9  840.45  1566.8  849.81  1589.1  868.47  1601.4  871.93  1660.7  896.83
#Mann= 13 ,-1,0
       0      .1       0     180     .06       0     320     .05       0
  656.57      .1       0  862.31     .05       0   947.8    .045       0
  969.18     .05       0  1074.2     .06       0  1094.2     .05       0
  1204.2     .07       0  1244.2     .05       0 1320.47     .08       0
 1430.47      .1       0
Bank Sta=947.8,969.18
XS Rating Curve= 0 ,0
Exp/Cntr(USF)=0,0
Exp/Cntr=0.3,0.1
LCMann Table=0

Chan Stop Cuts=-1
Use User Specified Reach Order=0
Composite Channel Slope=5